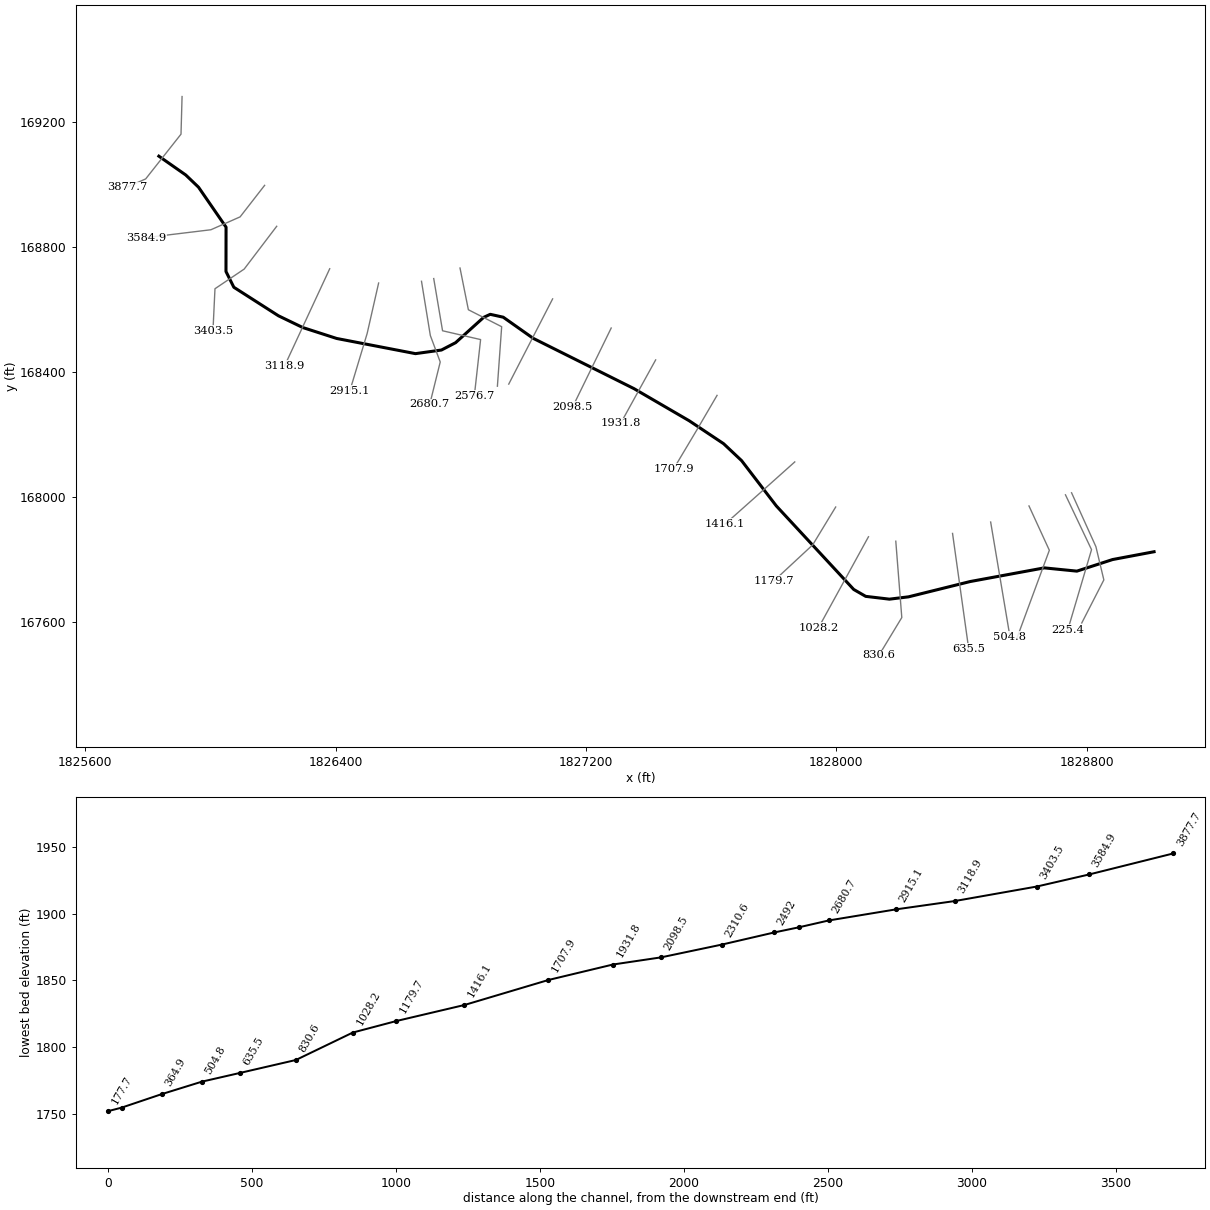
--- LAURELRN.prj (project) ---

Proj Title=LAURELRN
Current Plan=p01
Default Exp/Contr=0,0
English Units
Geom File=g01
Flow File=f01
Plan File=p01
BEGIN DESCRIPTION:
END DESCRIPTION:
DSS Export Rating Curves= 0
DSS Export Rating Curve Sorted= 0
DSS Export Volume Flow Curves= 0
DXF OffsetX= 0
DXF OffsetY= 0
DXF ScaleX= 0
DXF ScaleY= 0

--- LAURELRN.p01 (plan) ---

Plan Title=Floodplain
Program Version=4.00
Geom File=g01
Flow File=f01
K Sum by GR=0
Std Step Tol=0.01
Critical Tol=0.01
Num of Std Step Trials=20
Max Error Tol=0.3
Flow Tol Ratio=0.001
Split Flow NTrial=30
Split Flow Tol=0.02
Split Flow Ratio=0.02
Log Output Level=0
Friction Slope Method=1
Unsteady Friction Slope Method=2
Unsteady Bridges Friction Slope Method=1
Global Log Level=0
CheckData=False
Run HTab=0
Run UNet=0
Run PostProcess=0
UNET Theta=0
UNET Theta Warmup=0
UNET ZTol=0
UNET ZSATol=0
UNET MxIter=0
UNET MaxInSteps=0
UNET DtIC=0
UNET DtMin=0
UNET MaxCRTS=0
UNET WFStab=0
UNET SFStab=0
UNET WFX=0
UNET SFX=0
UNET DSS MLevel=0
UNET DZMax Abort=0
UNET Convert EG Bridges=0
UNET Use Existing IB Tables=0
UNET Froude Limit=0
UNET Froude Power=0
Write IC File=0
Echo Input=False
Echo Output=False
Write Detailed=0

--- LAURELRN.f01 (steady flow) ---

Flow Title=NFF Regression Equation
Program Version=4.10
Number of Profiles= 1
Profile Names=P100yr
River Rch & RM=LAURELRN,Main            ,3877.7
542.7843
River Rch & RM=LAURELRN,Main            ,3118.9
594.7962
River Rch & RM=LAURELRN,Main            ,504.8
630.6217
River Rch & RM=LAURELRN,Main            ,225.4
632.6089
Boundary for River Rch & Prof#=LAURELRN,Main            , 1
Up Type= 0
Dn Type= 3
Dn Slope=0.056
DSS Import GetInterval= 0
DSS Import GetPeak= 0
DSS Import FillOption= 0

--- LAURELRN.g01 (geometry) ---

Geom Title=USGS 10m DEM
Program Version=4.10

River Reach=LAURELRN        ,Main
Reach XY= 30
      1825835.65      169092.133      1825921.62      169031.861
     1825962.404      168992.739     1826050.329       168864.92
     1826050.102      168722.941     1826075.206       168672.51
     1826217.823      168581.084     1826295.473      168543.554
     1826403.631        168508.6     1826655.429      168460.012
     1826738.373      168471.566     1826783.607      168495.103
     1826873.206      168576.121     1826894.302      168585.867
     1826935.779      168576.658       1827031.3      168509.123
     1827353.283      168348.078     1827529.918      168245.084
     1827639.648       168171.79      1827697.13      168117.572
     1827808.115      167972.548     1828055.425      167705.095
     1828093.617      167683.079     1828169.383        167674.1
     1828230.542      167681.545     1828427.294      167730.484
       1828664.1      167774.234     1828768.267      167763.818
       1828882.4      167800.926     1829014.813      167825.896

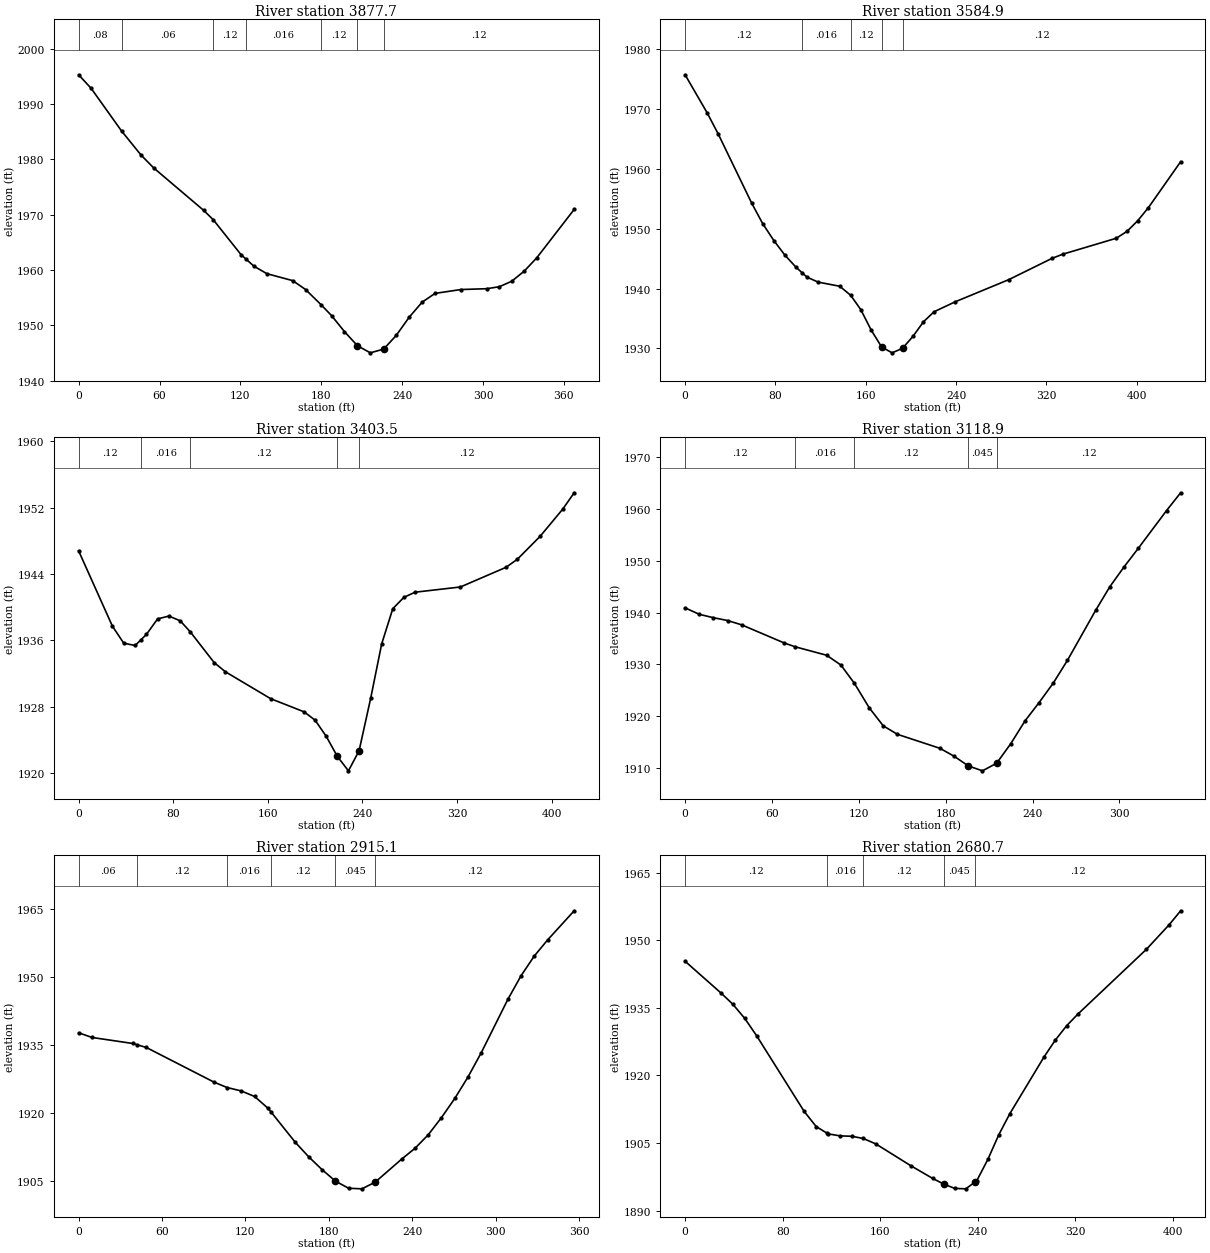
Type RM Length L Ch R = 1 ,3877.7  ,311.1,292.8,274.4
XS GIS Cut Line= 4
     1825909.816      169282.986     1825906.439      169162.569
     1825793.592       169019.34     1825734.353      168993.094
#Sta/Elev= 30
       0 1995.31     9.3 1992.85   31.821985.149    46.3 1980.79    55.6 1978.48
    92.7  1970.8   99.861969.096   120.5 1962.77  123.981962.012   130.1 1960.68
   139.7 1959.33   158.8 1958.08   168.4 1956.46  179.731953.752   187.6 1951.76
   197.2 1948.86   206.8 1946.31   216.4 1945.02   226.3  1945.7   235.6 1948.17
   245.2 1951.46   254.8 1954.18   264.4 1955.77   283.6 1956.47   302.8 1956.62
   312.1 1956.98   321.3 1957.97   330.6 1959.81   339.8 1962.19   367.6 1970.96
#Mann= 7 ,-1 , 0
       0     .08       0   31.82     .06       0   99.86     .12       0
  123.98    .016       0  179.73     .12       0   206.8    .045       0
   226.3     .12       0
Bank Sta=206.8,226.3
XS Rating Curve= 0 ,0
Exp/Cntr=0.3,0.1

Type RM Length L Ch R = 1 ,3584.9  ,174.6,181.4,187.8
XS GIS Cut Line= 4
     1826173.509      168998.666     1826095.242      168897.812
     1826001.926      168856.579     1825794.348      168831.368
#Sta/Elev= 30
       0 1975.73    19.6 1969.35    29.5 1965.77    58.9  1954.3    68.7 1950.86
    78.6 1948.02    88.4 1945.58    98.2 1943.57  103.89  1942.6     108  1941.9
   117.8 1941.08   136.9 1940.39  146.621938.878   155.5  1936.5   164.8 1933.06
     174 1930.24   183.3 1929.26   192.6 1930.02   201.9 1932.05   211.1 1934.45
   220.4 1936.12   239.2 1937.79   286.7  1941.5   324.7 1945.03   334.2 1945.73
   381.8 1948.41   391.3 1949.56   400.8 1951.34   410.3 1953.54   438.8  1961.2
#Mann= 5 ,-1 , 0
       0     .12       0  103.89    .016       0  146.62     .12       0
     174    .045       0   192.6     .12       0
Bank Sta=174,192.6
XS Rating Curve= 0 ,0
Exp/Cntr=0.3,0.1

Type RM Length L Ch R = 1 ,3403.5  ,264.1,284.6,305.1
XS GIS Cut Line= 4
     1826212.127        168867.7     1826108.262      168730.711
     1826014.946      168667.777     1826008.519      168533.336
#Sta/Elev= 30
       0 1946.79    28.6 1937.69    38.2 1935.64    47.8 1935.37   52.861936.078
    57.3  1936.7    66.8 1938.58    76.4 1938.92      86 1938.34   94.61 1936.98
   114.6 1933.31   124.2 1932.19   162.4 1928.95   190.7 1927.36     200 1926.35
   209.4 1924.41   218.8 1921.98   228.2 1920.24   237.2 1922.67     247    1929
   256.3 1935.56   265.7 1939.81   275.1 1941.18   284.5  1941.8   322.9 1942.43
   361.4  1944.8     371 1945.77   390.2 1948.53   409.4 1951.82   419.1  1953.8
#Mann= 5 ,-1 , 0
       0     .12       0   52.86    .016       0   94.61     .12       0
   218.8    .045       0   237.2     .12       0
Bank Sta=218.8,237.2
XS Rating Curve= 0 ,0
Exp/Cntr=0.3,0.1

Type RM Length L Ch R = 1 ,3118.9  ,198.4,203.9,209.2
XS GIS Cut Line= 2
     1826381.471      168731.771     1826237.541      168421.154
#Sta/Elev= 29
       0 1940.91     9.8 1939.66    19.6    1939    29.3 1938.46    39.1 1937.62
    68.5 1934.11   76.171933.367    97.8 1931.74   107.6 1929.85  116.971926.303
   127.2 1921.57   136.9 1918.08   146.7 1916.44   176.1 1913.73   185.8 1912.21
   195.6 1910.34   205.4 1909.38   215.2 1910.85     225 1914.65   234.8 1919.04
   244.5 1922.58   254.3 1926.35   264.1 1930.75   283.7 1940.48   293.4    1945
   303.2 1948.83     313 1952.41   332.6 1959.74   342.3 1963.17
#Mann= 5 ,-1 , 0
       0     .12       0   76.17    .016       0  116.97     .12       0
   195.6    .045       0   215.2     .12       0
Bank Sta=195.6,215.2
XS Rating Curve= 0 ,0
Exp/Cntr=0.3,0.1

Type RM Length L Ch R = 1 ,2915.1  ,210.1,234.4,257.9
XS GIS Cut Line= 3
     1826537.698      168686.046     1826501.058      168524.548
     1826446.025      168341.795
#Sta/Elev= 30
       0 1937.64     9.7 1936.61      39 1935.28   42.31 1934.98    48.7  1934.4
    97.4 1926.74  106.791925.552   116.9  1924.8   126.6 1923.57   136.4 1920.92
  138.151920.251   155.9 1913.43   165.6 1910.21   175.1 1907.41   184.7 1904.88
   194.2 1903.29   203.8 1903.16   213.3 1904.63   232.4 1909.73     242 1912.12
   251.5  1915.1     261 1918.89   270.6 1923.13   280.1 1927.87   289.7 1933.27
   308.8 1945.04   318.3 1950.26   327.8 1954.61   337.4 1958.17   356.5 1964.61
#Mann= 6 ,-1 , 0
       0     .06       0   42.31     .12       0  106.79    .016       0
  138.15     .12       0   184.7    .045       0   213.3     .12       0
Bank Sta=184.7,213.3
XS Rating Curve= 0 ,0
Exp/Cntr=0.3,0.1

Type RM Length L Ch R = 1 ,2680.7  ,61.7,103.9,144.5
XS GIS Cut Line= 4
     1826674.669      168691.649      1826702.88      168518.038
     1826734.506      168433.276     1826700.882       168297.33
#Sta/Elev= 30
       0 1945.37    29.3 1938.35    39.1 1935.84    48.9 1932.68    58.6 1928.85
    97.7    1912   107.5 1908.65  116.09 1907.23   117.3 1907.03     127 1906.59
   136.8 1906.49  146.161906.003   156.4  1904.8   184.9 1899.99     203 1897.14
   212.1 1895.88   221.1 1894.92   230.2 1894.82   237.6  1896.3   239.2 1896.62
   248.3 1901.36   257.3 1906.85   266.4 1911.55   294.4 1924.13   303.7 1927.89
     313 1931.08   322.4  1933.7   378.4 1948.04   397.1 1953.51   406.4 1956.58
#Mann= 5 ,-1 , 0
       0     .12       0  116.09    .016       0  146.16     .12       0
   212.1    .045       0   237.6     .12       0
Bank Sta=212.1,237.6
XS Rating Curve= 0 ,0
Exp/Cntr=0.3,0.1

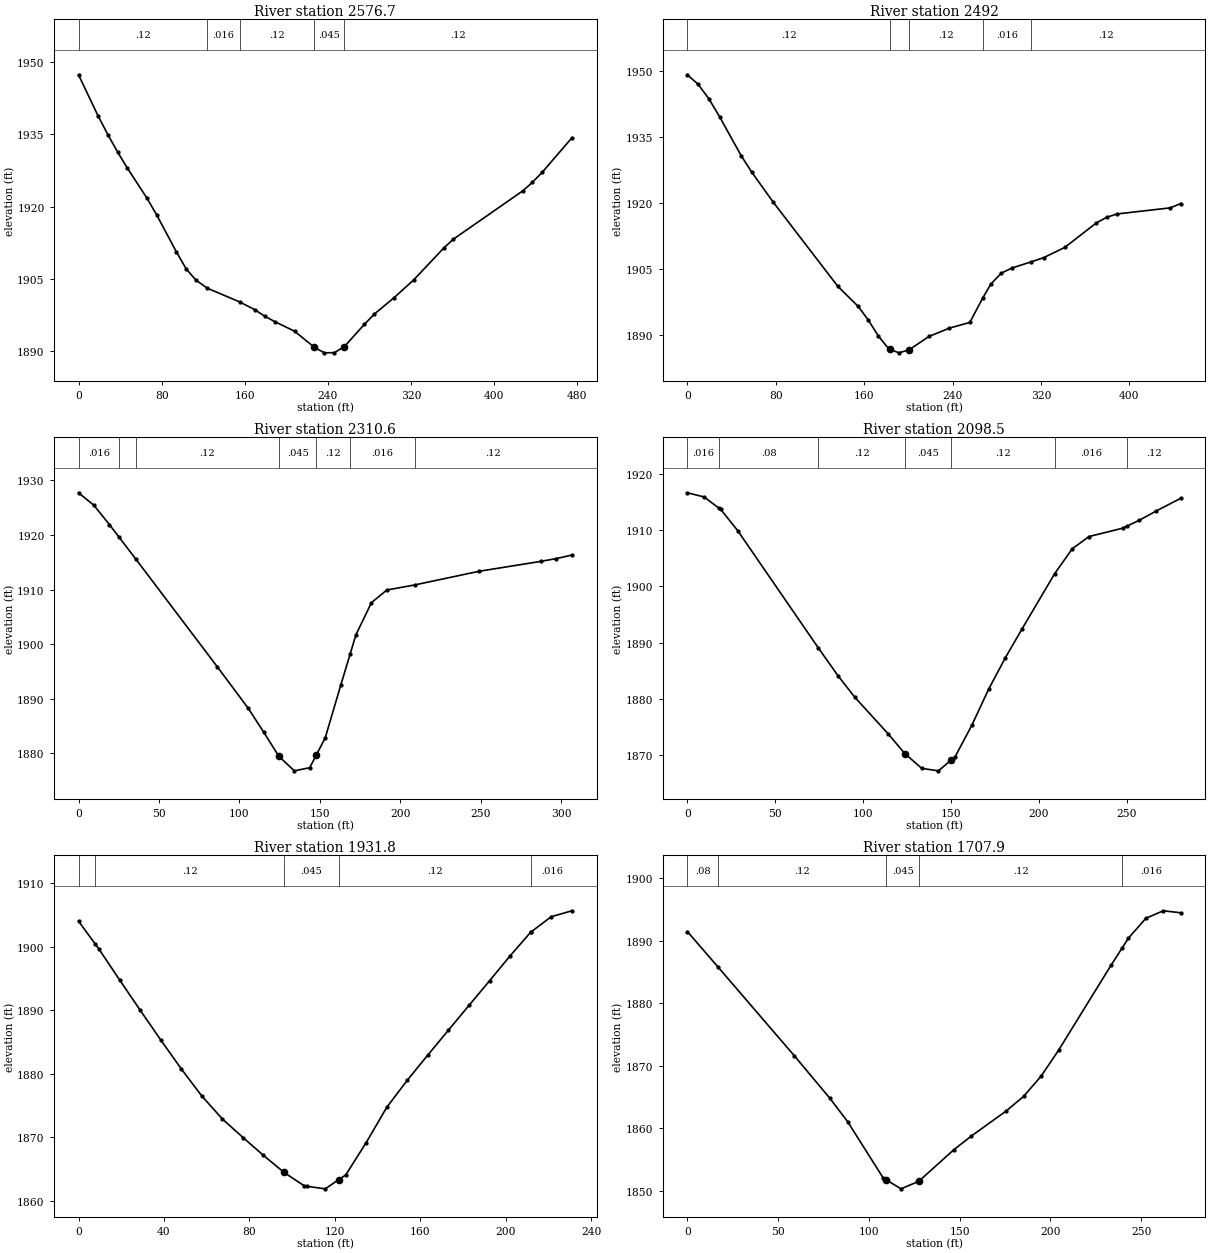
Type RM Length L Ch R = 1 ,2576.7  ,98.5,84.7,93.3
XS GIS Cut Line= 4
     1826713.731      168700.329     1826741.943      168533.229
     1826863.471      168505.017     1826843.536      168325.607
#Sta/Elev= 30
       0 1947.36    18.8 1938.83    28.2 1934.96    37.7  1931.3    47.1 1927.97
    65.9 1921.75    75.3 1918.26    94.2 1910.61   103.6  1907.1     113 1904.76
  124.051903.086  154.951900.258   169.5 1898.65   179.1 1897.29   188.7 1896.18
   207.8 1894.18     227 1890.83   236.6 1889.69   246.2 1889.73   255.8 1890.99
     275  1895.6   284.6 1897.72   303.7 1901.15   322.7 1904.86   351.2 1911.38
   360.7 1913.27   427.2 1923.25   436.7 1925.05   446.2 1927.15   474.7 1934.29
#Mann= 5 ,-1 , 0
       0     .12       0  124.05    .016       0  154.95     .12       0
     227    .045       0   255.8     .12       0
Bank Sta=227,255.8
XS Rating Curve= 0 ,0
Exp/Cntr=0.3,0.1

Type RM Length L Ch R = 1 ,2492    ,241,181.4,100.5
XS GIS Cut Line= 4
     1826797.696      168734.063     1826824.408      168600.503
     1826930.745       168546.25     1826917.142      168355.804
#Sta/Elev= 30
       0 1949.18     9.7 1947.03    19.5  1943.7    29.2 1939.62    48.6 1930.79
    58.4 1926.96    77.8 1920.14   136.2    1901   154.6 1896.44   163.8 1893.31
   172.9 1889.69   182.1 1886.82   183.1 1886.72   191.3 1885.87   200.5 1886.54
   218.8 1889.62   237.2  1891.5   255.6 1892.79  267.211898.312   274.7 1901.55
   284.2 1904.03   293.8 1905.19  310.681906.547   322.4 1907.54   341.5 1909.86
   370.1 1915.45   379.7 1916.76   389.2  1917.5     437 1918.88   446.5 1919.85
#Mann= 5 ,-1 , 0
       0     .12       0   183.1    .045       0   200.5     .12       0
  267.21    .016       0  310.68     .12       0
Bank Sta=183.1,200.5
XS Rating Curve= 0 ,0
Exp/Cntr=0.3,0.1

Type RM Length L Ch R = 1 ,2310.6  ,211.4,212.1,213
XS GIS Cut Line= 2
     1827093.505      168635.225     1826953.383      168362.555
#Sta/Elev= 23
       0 1927.72     9.6 1925.42    19.2  1921.9   24.981919.673    35.71915.542
    86.2 1895.88   105.4  1888.3     115 1883.94   124.5 1879.48   134.1 1876.82
   143.7  1877.4   147.7 1879.68   153.3 1882.86   162.9 1892.45  168.731898.145
   172.4 1901.73     182  1907.6   191.6 1909.92  208.791910.843   249.1 1913.36
   287.4 1915.17     297 1915.68   306.6 1916.32
#Mann= 7 ,-1 , 0
       0    .016       0   24.98     .08       0    35.7     .12       0
   124.5    .045       0   147.7     .12       0  168.73    .016       0
  208.79     .12       0
Bank Sta=124.5,147.7
XS Rating Curve= 0 ,0
Exp/Cntr=0.3,0.1

Type RM Length L Ch R = 1 ,2098.5  ,168.6,166.7,164.9
XS GIS Cut Line= 3
     1827280.663      168542.021     1827159.593      168293.717
     1827157.867      168289.498
#Sta/Elev= 26
       0 1916.65     9.5 1915.91   17.911913.936      19 1913.68    28.6 1909.94
   74.62 1889.03    85.7 1884.13    95.3  1880.3   114.3 1873.78   123.8 1870.27
   133.4 1867.65   142.9 1867.21     150 1869.09   152.4 1869.73   161.9 1875.31
   171.5 1881.75     181 1887.33   190.5 1892.45   209.11902.297   219.1 1906.71
   228.6 1908.87   247.7 1910.35  250.431910.755   257.2 1911.76   266.7 1913.39
   280.8 1915.67
#Mann= 7 ,-1 , 0
       0    .016       0   17.91     .08       0   74.62     .12       0
   123.8    .045       0     150     .12       0   209.1    .016       0
  250.43     .12       0
Bank Sta=123.8,150
XS Rating Curve= 0 ,0
Exp/Cntr=0.3,0.1

Type RM Length L Ch R = 1 ,1931.8  ,224.8,223.9,222.7
XS GIS Cut Line= 2
     1827422.664      168439.981     1827311.254      168237.682
#Sta/Elev= 29
       0 1904.05    7.941900.403     9.6 1899.64    19.2 1894.81    28.9 1890.01
    38.5 1885.33    48.1 1880.78    57.7 1876.51    67.4 1872.86      77 1869.96
    86.6 1867.14    96.2 1864.46   105.8 1862.32   106.9 1862.27   115.5 1861.87
   121.9 1863.33   125.1 1864.06   134.7 1869.17   144.3 1874.71     154 1879.02
   163.6 1882.98   173.2 1886.88   182.8 1890.77   192.5 1894.68   202.1  1898.6
   211.7 1902.31  211.951902.374   221.3 1904.75     231 1905.69
#Mann= 5 ,-1 , 0
       0    .016       0    7.94     .12       0    96.2    .045       0
   121.9     .12       0  211.95    .016       0
Bank Sta=96.2,121.9
XS Rating Curve= 0 ,0
Exp/Cntr=0.3,0.1

Type RM Length L Ch R = 1 ,1707.9  ,303.6,291.8,280.3
XS GIS Cut Line= 3
     1827618.798      168326.413     1827554.578      168216.276
     1827480.727      168092.253
#Sta/Elev= 21
       0 1891.44   17.041885.719    58.8 1871.62    78.5 1864.78    88.3 1861.04
   107.9 1852.03   109.7 1851.71   117.7  1850.3   127.5 1851.51   146.7 1856.53
   156.4 1858.73   175.6 1862.74   185.2 1865.07   194.8 1868.29   204.5 1872.46
   233.4 1886.05  239.491888.803     243 1890.39   252.6 1893.56   262.2 1894.76
   271.8 1894.44
#Mann= 5 ,-1 , 0
       0     .08       0   17.04     .12       0   109.7    .045       0
   127.5     .12       0  239.49    .016       0
Bank Sta=109.7,127.5
XS Rating Curve= 0 ,0
Exp/Cntr=0.3,0.1

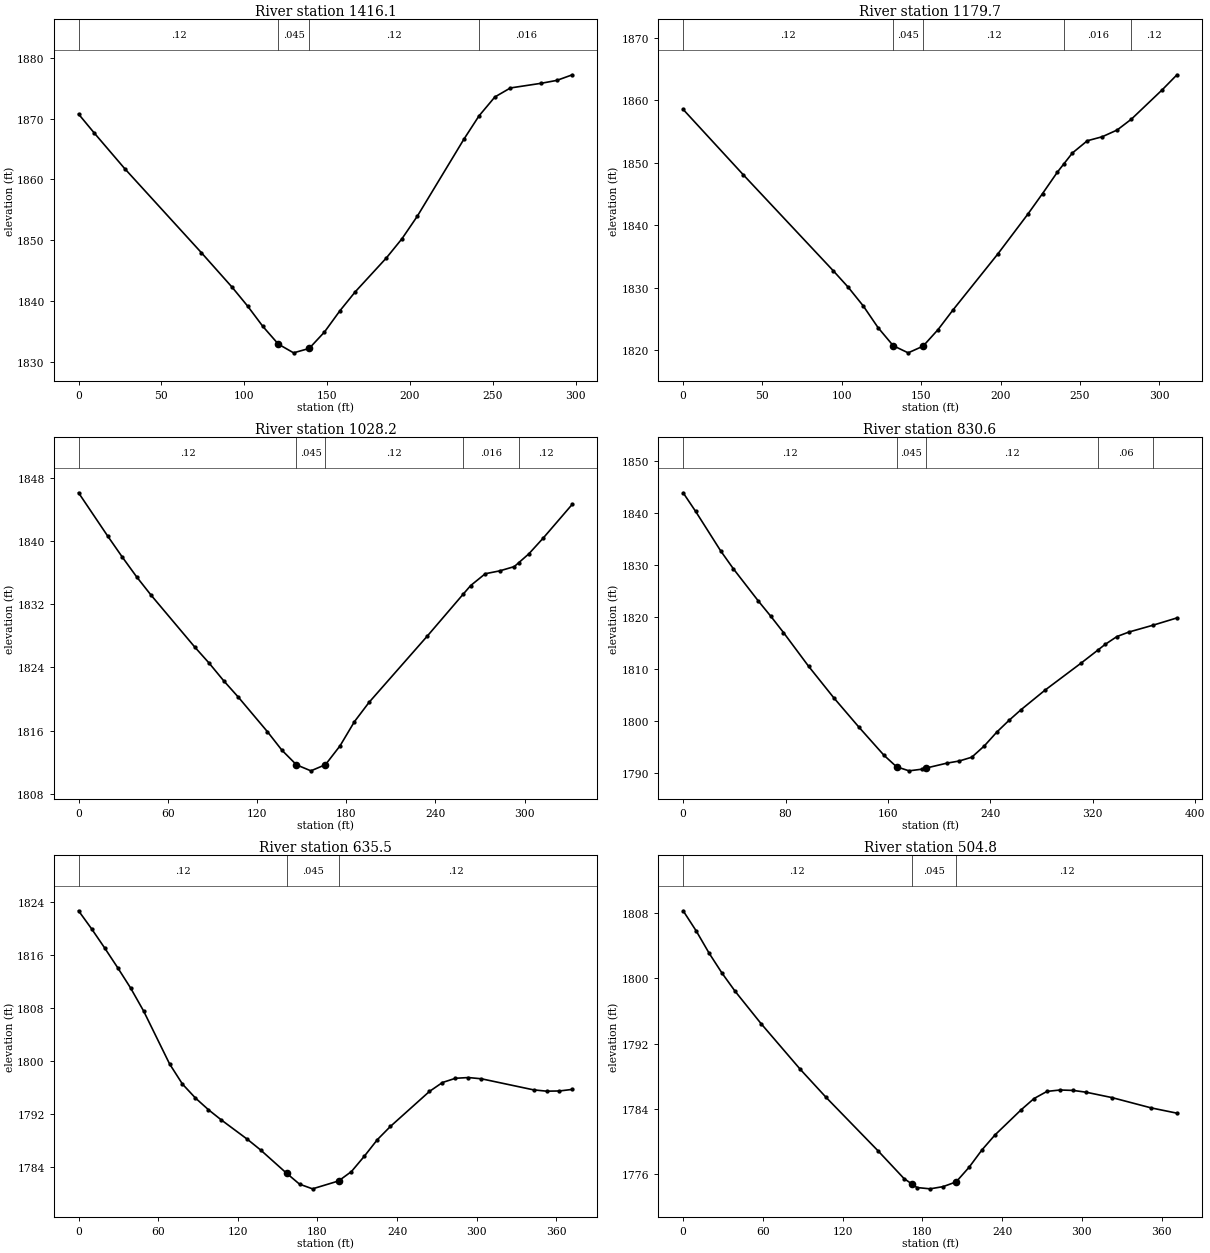
Type RM Length L Ch R = 1 ,1416.1  ,225.1,236.3,237
XS GIS Cut Line= 3
     1827867.005      168113.375     1827756.463      168014.374
     1827644.699      167914.786
#Sta/Elev= 23
       0 1870.73     9.3 1867.68    27.8  1861.8    74.2 1847.98    92.8  1842.3
     102 1839.26   111.3 1835.89   120.6    1833   129.8 1831.57   139.2 1832.29
   148.4 1834.97   157.8 1838.48   167.1  1841.6   185.8 1847.13   195.2 1850.27
   204.5 1853.98   232.6  1866.6  241.741870.431   251.3 1873.53   260.7 1875.01
   279.4 1875.78   288.7 1876.25   298.1 1877.17
#Mann= 4 ,-1 , 0
       0     .12       0   120.6    .045       0   139.2     .12       0
  241.74    .016       0
Bank Sta=120.6,139.2
XS Rating Curve= 0 ,0
Exp/Cntr=0.3,0.1

Type RM Length L Ch R = 1 ,1179.7  ,149.9,151.5,164.3
XS GIS Cut Line= 3
     1827997.744      167969.029     1827924.206      167847.749
     1827800.216       167732.41
#Sta/Elev= 23
       0 1858.55    37.8 1848.11    94.6 1832.72     104 1830.09   113.5 1827.09
   122.9 1823.59   132.4 1820.72   141.8 1819.58   151.2 1820.65   160.6 1823.29
   170.1 1826.46   198.3 1835.41   217.1 1841.74   226.5 1845.08   235.9 1848.53
  239.89 1849.82   245.3 1851.57   254.7 1853.53   264.1 1854.17   273.5 1855.25
   282.51856.993   301.8 1861.66   311.2 1864.09
#Mann= 5 ,-1 , 0
       0     .12       0   132.4    .045       0   151.2     .12       0
  239.89    .016       0   282.5     .12       0
Bank Sta=132.4,151.2
XS Rating Curve= 0 ,0
Exp/Cntr=0.3,0.1

Type RM Length L Ch R = 1 ,1028.2  ,175.6,197.6,218.9
XS GIS Cut Line= 2
     1828102.488      167873.856     1827942.876      167582.526
#Sta/Elev= 27
       0 1846.08    19.5 1840.64    29.3 1837.99    39.1 1835.45    48.8 1833.14
    78.2 1826.58    87.9 1824.54    97.7 1822.31   107.5 1820.25     127  1815.9
   136.8 1813.55   146.6  1811.7   156.3 1810.94   166.1 1811.72   175.9  1814.1
   185.6 1817.16   195.4 1819.59   234.5 1827.95  258.691833.255   263.8 1834.36
   273.6 1835.85   283.3 1836.21   293.1 1836.75  296.061837.236   302.9 1838.36
   312.6 1840.36   332.2 1844.64
#Mann= 5 ,-1 , 0
       0     .12       0   146.6    .045       0   166.1     .12       0
  258.69    .016       0  296.06     .12       0
Bank Sta=146.6,166.1
XS Rating Curve= 0 ,0
Exp/Cntr=0.3,0.1

Type RM Length L Ch R = 1 ,830.6   ,192.8,195.1,197.4
XS GIS Cut Line= 3
     1828189.755      167859.644     1828208.957       167615.26
     1828136.215      167494.818
#Sta/Elev= 30
       0 1843.82     9.8 1840.23    29.4 1832.63    39.2 1829.23    58.8 1823.01
    68.6 1820.06    78.4 1816.97      98 1810.49   117.7 1804.43   137.3  1798.8
   156.9 1793.39   166.7 1791.18   176.5  1790.4   186.3 1790.71   189.4 1790.91
   205.9 1791.87   215.7 1792.29   225.5 1793.02   235.3 1795.19   245.1 1797.86
   254.5 1800.08   263.9 1802.13   282.7  1805.9   310.8 1811.08  324.051813.605
   329.6 1814.68   338.9  1816.2   348.3 1817.07  367.251818.391   385.8 1819.78
#Mann= 5 ,-1 , 0
       0     .12       0   166.7    .045       0   189.4     .12       0
  324.05     .06       0  367.25    .016       0
Bank Sta=166.7,189.4
XS Rating Curve= 0 ,0
Exp/Cntr=0.3,0.1

Type RM Length L Ch R = 1 ,635.5   ,129.6,130.7,131.7
XS GIS Cut Line= 2
     1828371.059      167884.487     1828422.538      167515.928
#Sta/Elev= 30
       0 1822.72     9.8    1820    19.6 1817.12    29.4 1814.14    39.2 1811.05
      49 1807.57    68.6 1799.56    78.3 1796.51    88.1  1794.4    97.9 1792.63
   107.7 1791.07   127.3 1788.15   137.1 1786.56   156.7 1783.04   166.5 1781.38
   176.3 1780.67   195.9 1781.86   205.6 1783.28   215.4 1785.62   225.2 1788.12
     235 1790.11   264.4  1795.4   274.2 1796.75     284 1797.39   293.8  1797.5
   303.6 1797.31   342.8 1795.64   352.6 1795.44   362.3 1795.47   372.1 1795.71
#Mann= 3 ,-1 , 0
       0     .12       0   156.7    .045       0   195.9     .12       0
Bank Sta=156.7,195.9
XS Rating Curve= 0 ,0
Exp/Cntr=0.3,0.1

Type RM Length L Ch R = 1 ,504.8   ,160.3,140,118.3
XS GIS Cut Line= 2
     1828492.796       167921.04     1828554.365      167554.557
#Sta/Elev= 27
       0 1808.29     9.8 1805.83    19.6 1803.08    29.3 1800.64    39.1 1798.43
    58.7 1794.45      88 1788.89   107.6 1785.42   146.7 1778.87   166.2 1775.48
     172 1774.83     176 1774.38   185.8 1774.22   195.6 1774.49   205.4 1775.07
   215.2 1776.87   224.9    1779   234.7 1780.83   254.3  1783.9     264 1785.28
   273.8 1786.16   283.6 1786.33   293.4 1786.28   303.2 1786.06   322.7  1785.4
   352.1 1784.14   371.6 1783.49
#Mann= 3 ,-1 , 0
       0     .12       0     172    .045       0   205.4     .12       0
Bank Sta=172,205.4
XS Rating Curve= 0 ,0
Exp/Cntr=0.3,0.1

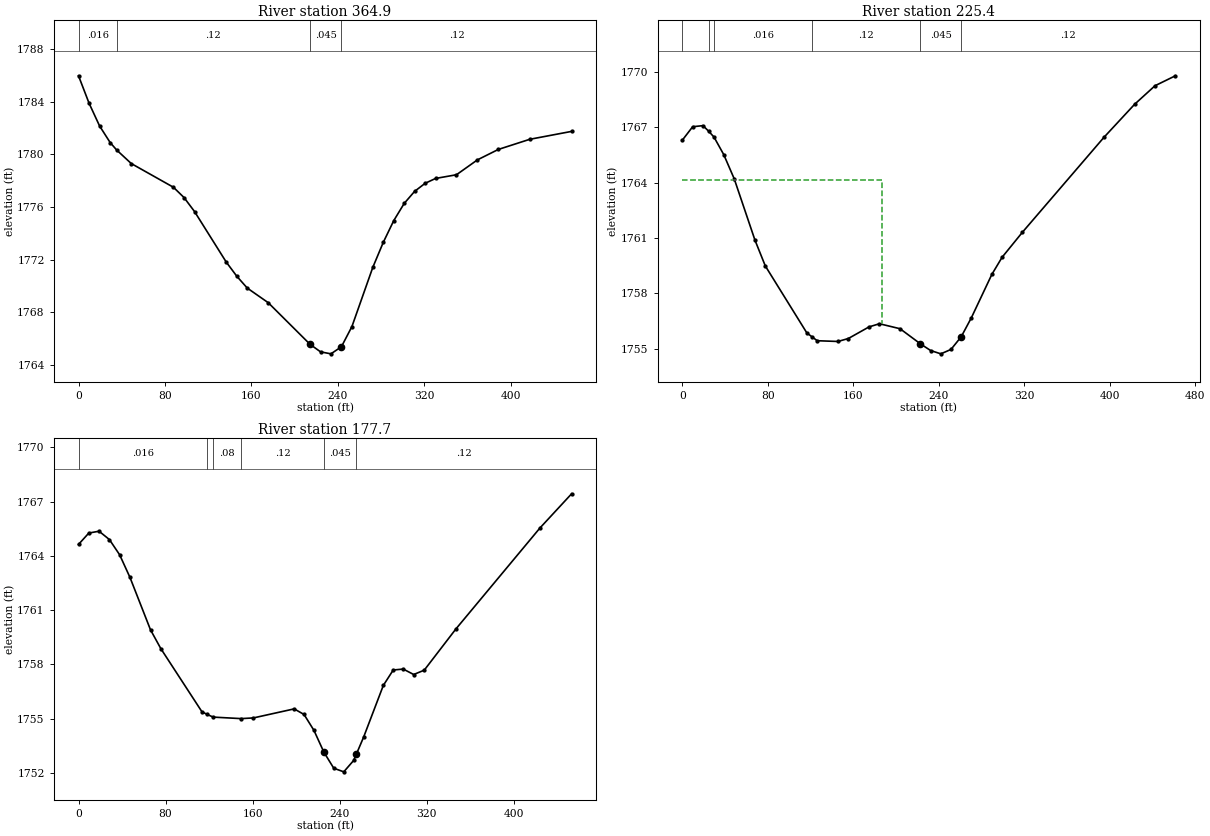
Type RM Length L Ch R = 1 ,364.9   ,138.9,139.5,142.1
XS GIS Cut Line= 3
     1828615.232      167972.498     1828680.273      167830.563
     1828576.604      167549.104
#Sta/Elev= 30
       0 1785.96     9.8 1783.87    19.5 1782.15    29.3 1780.89   35.38 1780.32
    48.8  1779.3    87.8  1777.5    97.6 1776.72   107.3 1775.66   136.6 1771.83
   146.4 1770.75   156.1 1769.85   175.5 1768.74   214.2 1765.58   223.9 1765.01
   233.5 1764.86   243.2  1765.4   252.9 1766.93   272.2 1771.42   281.9 1773.32
   291.6 1774.97   301.3 1776.28   310.9 1777.19   320.6  1777.8   330.3 1778.17
   349.6 1778.45     369 1779.58   388.3 1780.37   417.4 1781.14   456.1 1781.74
#Mann= 4 ,-1 , 0
       0    .016       0   35.38     .12       0   214.2    .045       0
   243.2     .12       0
Bank Sta=214.2,243.2
XS Rating Curve= 0 ,0
Exp/Cntr=0.3,0.1

Type RM Length L Ch R = 1 ,225.4   ,25.2,47.7,69.4
XS GIS Cut Line= 3
     1828731.769      168008.088     1828815.036      167832.592
     1828739.364      167576.231
#Sta/Elev= 30
       0  1766.3     9.7 1767.03    19.4 1767.09   24.861766.775   29.671766.471
    38.8 1765.52    48.6 1764.21      68 1760.89    77.7 1759.49   116.6 1755.86
  121.581755.644   126.3 1755.44   145.7  1755.4   155.4 1755.56   174.8 1756.19
   184.5 1756.36   203.8 1756.09   222.9 1755.27   232.4 1754.91     242 1754.73
   251.5 1754.97   261.1 1755.66   270.6 1756.69   289.7 1759.03   299.3 1759.96
   318.4 1761.32   394.7 1766.46   423.4 1768.25   442.4 1769.25   461.5 1769.79
#Mann= 6 ,-1 , 0
       0    .016       0   24.86     .12       0   29.67    .016       0
  121.58     .12       0   222.9    .045       0   261.1     .12       0
#XS Ineff= 2 , 0
          187.26 1764.16
Permanent Ineff=
       F       F
Bank Sta=222.9,261.1
XS Rating Curve= 0 ,0
Exp/Cntr=0.3,0.1

Type RM Length L Ch R = 1 ,177.7   ,179.4,177.7,175.8
XS GIS Cut Line= 4
       1828751.3      168014.599     1828829.036       167842.14
     1828854.382      167735.736     1828783.852      167597.932
#Sta/Elev= 30
       0 1764.63     9.5 1765.26    18.9 1765.36    28.4  1764.9    37.8 1764.06
    47.3 1762.81    66.2 1759.91    75.7 1758.87   113.5 1755.38  118.351755.232
  123.841755.085  149.581755.002   160.8 1755.04   198.3 1755.54   207.4 1755.23
   216.5 1754.35   225.6 1753.15   234.7 1752.26   243.9 1752.06     253 1752.69
   255.5 1753.04   262.1 1753.97   280.3 1756.84   289.4 1757.69   298.6 1757.74
   308.2 1757.44   317.9 1757.68   346.9 1759.95   424.3 1765.54   453.4 1767.43
#Mann= 6 ,-1 , 0
       0    .016       0  118.35     .12       0  123.84     .08       0
  149.58     .12       0   225.6    .045       0   255.5     .12       0
Bank Sta=225.6,255.5
XS Rating Curve= 0 ,0
Exp/Cntr=0.3,0.1

Chan Stop Cuts=-1
Use User Specified Reach Order=0
Composite Channel Slope=5